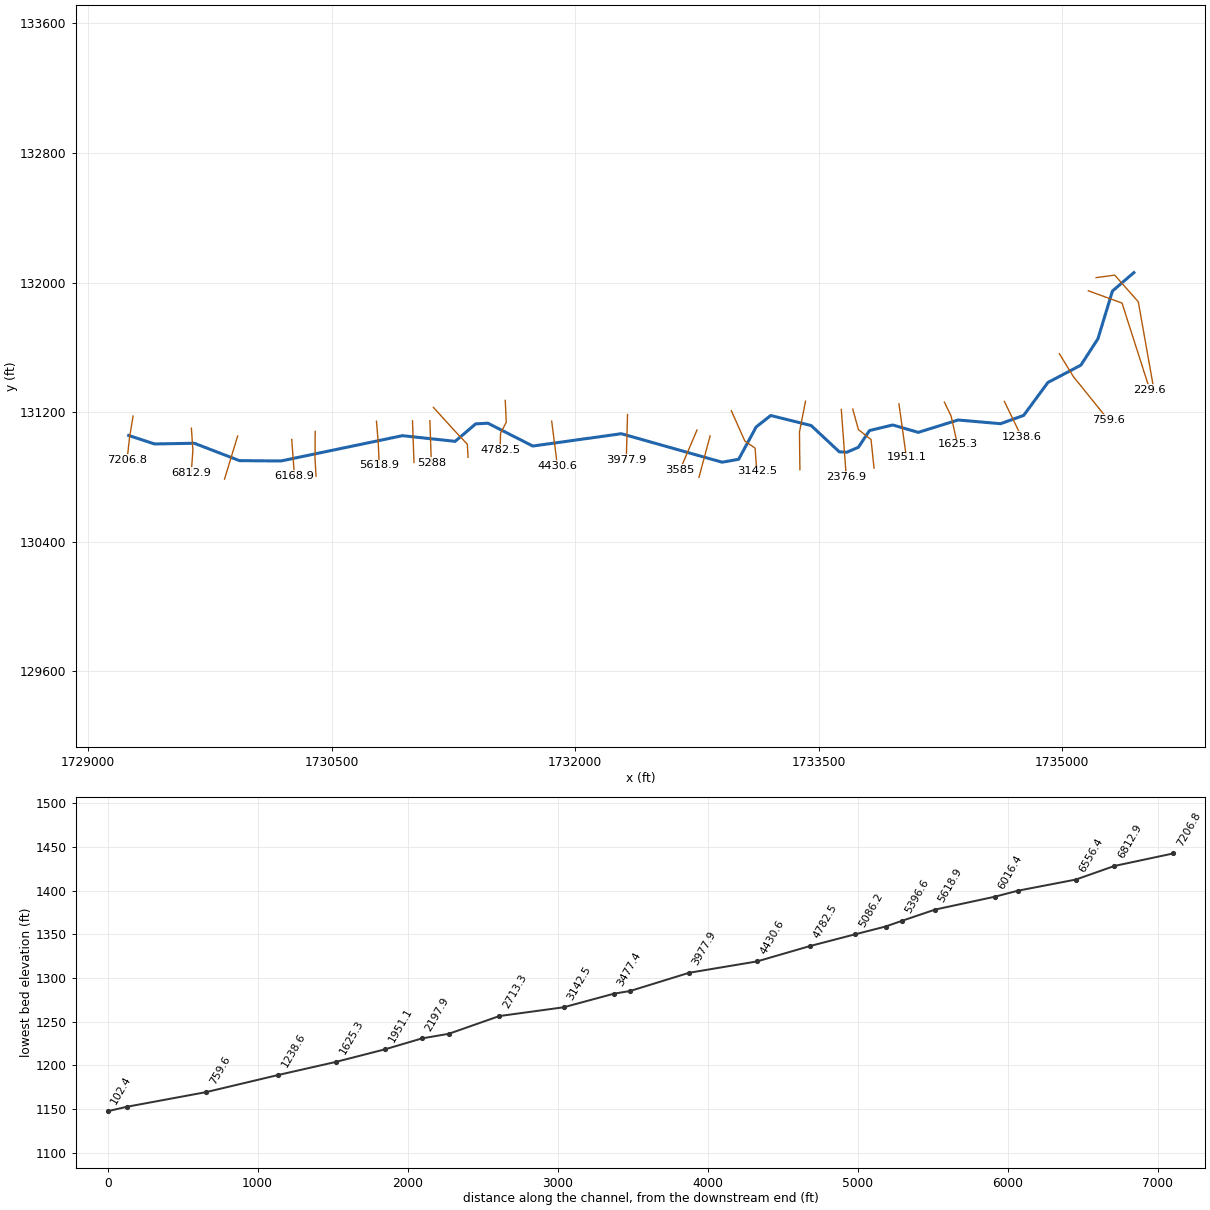
--- Oozley Branch.prj (project) ---

Proj Title=Oozley Branch
Current Plan=p01
Default Exp/Contr=0,0
English Units
Geom File=g01
Flow File=f01
Plan File=p01
BEGIN DESCRIPTION:
END DESCRIPTION:
DSS Export Rating Curves= 0
DSS Export Rating Curve Sorted= 0
DSS Export Volume Flow Curves= 0
DXF OffsetX= 0
DXF OffsetY= 0
DXF ScaleX= 0
DXF ScaleY= 0

--- Oozley Branch.p01 (plan) ---

Plan Title=Floodplain
Program Version=4.00
Geom File=g01
Flow File=f01
K Sum by GR=0
Std Step Tol=0.01
Critical Tol=0.01
Num of Std Step Trials=20
Max Error Tol=0.3
Flow Tol Ratio=0.001
Split Flow NTrial=30
Split Flow Tol=0.02
Split Flow Ratio=0.02
Log Output Level=0
Friction Slope Method=1
Unsteady Friction Slope Method=2
Unsteady Bridges Friction Slope Method=1
Global Log Level=0
CheckData=False
Run HTab=0
Run UNet=0
Run PostProcess=0
UNET Theta=0
UNET Theta Warmup=0
UNET ZTol=0
UNET ZSATol=0
UNET MxIter=0
UNET MaxInSteps=0
UNET DtIC=0
UNET DtMin=0
UNET MaxCRTS=0
UNET WFStab=0
UNET SFStab=0
UNET WFX=0
UNET SFX=0
UNET DSS MLevel=0
UNET DZMax Abort=0
UNET Convert EG Bridges=0
UNET Use Existing IB Tables=0
UNET Froude Limit=0
UNET Froude Power=0
Write IC File=0
Echo Input=False
Echo Output=False
Write Detailed=0

--- Oozley Branch.f01 (steady flow) ---

Flow Title=NFF Regression Equation
Program Version=4.00
Number of Profiles=1
Profile Names=P100yr
River Rch & RM=Oozley Branch,Main      ,7206.8
576.5446
River Rch & RM=Oozley Branch,Main      ,6556.4
606.7720
River Rch & RM=Oozley Branch,Main      ,5086.2
666.6361
River Rch & RM=Oozley Branch,Main      ,4782.5
857.2102
River Rch & RM=Oozley Branch,Main      ,3585
905.5026
River Rch & RM=Oozley Branch,Main      ,229.6
979.3600
Boundary for River Rch & Prof#=Oozley Branch,Main      ,1
Up Type=0
Dn Type=3
Dn Slope=0.03795

--- Oozley Branch.g01 (geometry) ---

Geom Title=Geometry
Program Version=4.00

River Reach=Oozley Branch   ,Main
Reach XY= 30
     1729248.804      131056.098     1729408.175      131003.758
     1729653.379      131007.964     1729931.303      130900.745
      1730186.76      130898.516     1730935.476      131054.813
     1731260.163      131019.724     1731386.382      131127.577
     1731461.677      131131.805     1731738.539      130990.809
     1732283.831      131066.879     1732904.637      130891.033
     1733006.698      130909.136     1733114.326      131108.628
     1733204.034      131179.247     1733453.192      131117.306
     1733626.785      130955.011     1733673.228      130952.687
     1733744.043      130982.969     1733812.705       131086.49
     1733955.958      131120.763     1734113.333      131075.276
     1734357.937      131151.601     1734620.169      131128.737
     1734762.404      131179.848      1734911.45      131382.983
     1735114.585       131489.96     1735219.758      131652.828
     1735309.306      131947.915     1735441.469      132061.495

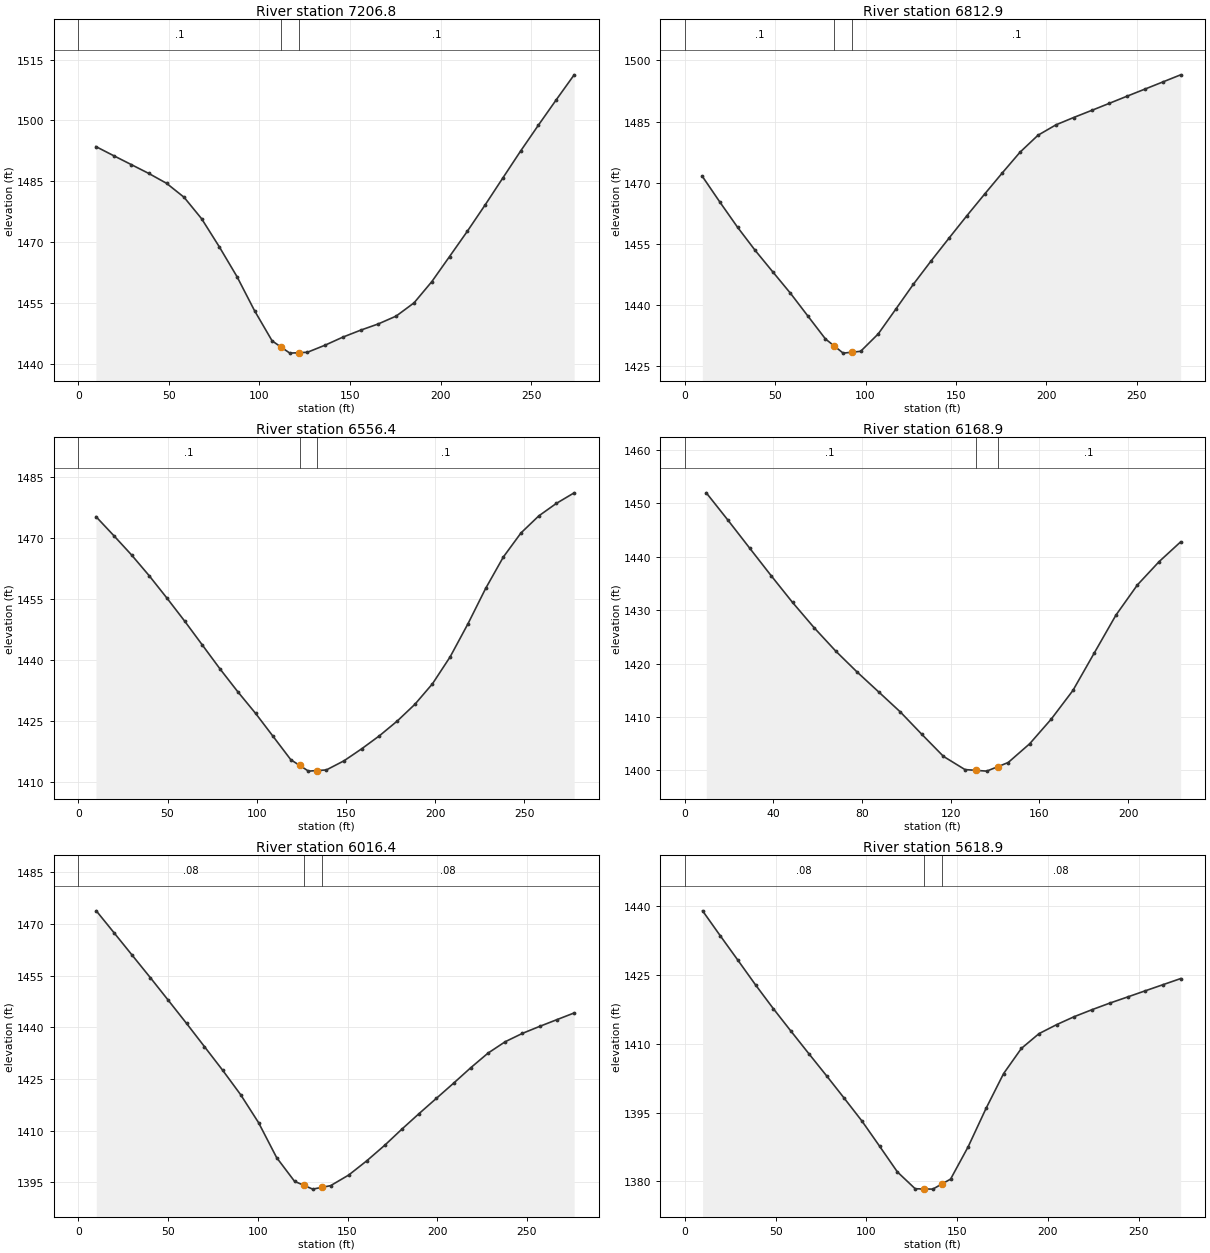
Type RM Length L Ch R = 1 ,7206.8  ,389.3,393.9,398.1
XS GIS Cut Line= 3
     1729276.031      131176.015     1729253.838      131041.594
     1729238.664      130904.923
#Sta/Elev= 30
     9.7 1493.55    19.5 1491.31    29.2 1489.12    38.9 1486.93    48.7  1484.5
    58.4 1481.05    68.1 1475.75    77.9  1468.8    87.6  1461.5    97.3  1453.1
     107 1445.66   111.8 1444.17   116.8 1442.63   121.8 1442.74   126.5 1442.84
   136.2 1444.58   146.1 1446.58   155.9 1448.29   165.7 1449.84   175.5 1451.76
   185.4 1455.03   195.2 1460.26     205 1466.45   214.8 1472.67   224.6 1479.14
   234.5 1485.87   244.3  1492.5   254.1 1498.86   263.9 1505.08   273.8 1511.24
#Mann= 3 , 0 , 0
       0      .1       0   111.8    .045       0   121.8      .1       0
Bank Sta=111.8,121.8
XS Rating Curve= 0 ,0
Exp/Cntr=0.3,0.1

Type RM Length L Ch R = 1 ,6812.9  ,263.9,256.5,249.2
XS GIS Cut Line= 3
     1729635.316      131100.799     1729644.444      130964.892
     1729634.423      130827.126
#Sta/Elev= 30
     9.7 1471.59    19.5 1465.22    29.2  1459.1    38.9 1453.45    48.6 1448.21
    58.4 1442.95    68.1 1437.33    77.8 1431.72    82.6 1430.02    87.6 1428.24
    92.6 1428.47    97.3 1428.69     107 1432.95   116.8 1439.07   126.5 1445.16
   136.2 1450.82   146.1  1456.4   155.9 1461.85   165.8  1467.2   175.7 1472.46
   185.5 1477.53   195.4 1481.67   205.3 1484.21   215.1 1486.01     225 1487.74
   234.9  1489.5   244.7 1491.25   254.6 1492.99   264.5 1494.74   274.3 1496.48
#Mann= 3 , 0 , 0
       0      .1       0    82.6    .045       0    92.6      .1       0
Bank Sta=82.6,92.6
XS Rating Curve= 0 ,0
Exp/Cntr=0.3,0.1

Type RM Length L Ch R = 1 ,6556.4  ,380.1,387.5,394.9
XS GIS Cut Line= 2
     1729920.244      131052.544     1729839.268      130786.698
#Sta/Elev= 30
     9.9 1475.31    19.9 1470.63    29.8  1465.9    39.7 1460.78    49.6  1455.3
    59.6  1449.6    69.5 1443.72    79.4 1437.84    89.3 1432.26    99.3 1426.92
   109.2 1421.21   119.1 1415.48     124  1414.1     129 1412.68     134 1412.83
     139 1412.97   148.9 1415.22   158.8 1418.17   168.7 1421.36   178.7 1424.99
   188.6 1429.11   198.5 1434.18   208.4 1440.81   218.4 1448.96   228.3 1457.65
   238.2 1465.37   248.1  1471.3   258.1  1475.5     268 1478.59   277.9 1481.17
#Mann= 3 , 0 , 0
       0      .1       0     124    .045       0     134      .1       0
Bank Sta=124,134
XS Rating Curve= 0 ,0
Exp/Cntr=0.3,0.1

Type RM Length L Ch R = 1 ,6168.9  ,154.1,152.5,150.8
XS GIS Cut Line= 2
     1730253.315      131031.154     1730270.121      130808.088
#Sta/Elev= 25
     9.7 1451.95    19.5 1446.82    29.2 1441.64    38.9 1436.48    48.6 1431.45
    58.4 1426.69    68.1 1422.34    77.8  1418.4    87.5 1414.69    97.3 1410.93
     107 1406.74   116.7 1402.64   126.4 1400.17   131.2 1400.03   136.2 1399.88
   141.2 1400.71   145.9 1401.49   155.6    1405   165.3  1409.6   175.1 1414.97
   184.8 1422.03   194.5 1429.06   204.2 1434.72     214 1439.08   223.7 1442.77
#Mann= 3 , 0 , 0
       0      .1       0   131.2    .045       0   141.2      .1       0
Bank Sta=131.2,141.2
XS Rating Curve= 0 ,0
Exp/Cntr=0.3,0.1

Type RM Length L Ch R = 1 ,6016.4  ,395.7,397.5,398.6
XS GIS Cut Line= 3
     1730397.936      131081.203     1730396.933      130910.454
     1730403.077      130805.091
#Sta/Elev= 30
      10 1473.76    20.1 1467.27    30.1 1460.83    40.2 1454.33    50.2 1447.77
    60.3 1441.11    70.3 1434.36    80.4 1427.54    90.4 1420.47   100.4 1412.35
   110.5 1402.19   120.5  1395.3   125.6 1394.16   130.6 1393.04   135.6 1393.54
   140.6 1394.05   150.7 1397.14   160.7 1401.24   170.8 1405.79   180.3 1410.44
   189.9 1414.96   199.5 1419.36   209.1 1423.76   218.7 1428.26   228.3 1432.49
   237.9  1435.8   247.5 1438.22   257.1 1440.25   266.7  1442.2   276.3 1444.14
#Mann= 3 , 0 , 0
       0     .08       0   125.6    .045       0   135.6     .08       0
Bank Sta=125.6,135.6
XS Rating Curve= 0 ,0
Exp/Cntr=0.3,0.1

Type RM Length L Ch R = 1 ,5618.9  ,223.2,222.3,222.1
XS GIS Cut Line= 3
     1730775.397      131143.968     1730786.535      131007.797
     1730792.362      130871.444
#Sta/Elev= 30
     9.8 1439.04    19.5 1433.62    29.3 1428.24      39 1422.87    48.8 1417.68
    58.6 1412.73    68.3 1407.89    78.1 1403.05    87.8 1398.17    97.6 1393.17
   107.3 1387.69   117.1 1382.08   126.9 1378.41   131.6 1378.37   136.6 1378.33
   141.6 1379.45   146.4 1380.52   156.1 1387.59   165.9 1395.92   175.6 1403.54
   185.4 1409.03   195.1 1412.25   204.9 1414.23   214.6 1415.97   224.4 1417.49
   234.1 1418.91   243.9 1420.25   253.6 1421.59   263.4 1422.93   273.1 1424.26
#Mann= 3 , 0 , 0
       0     .08       0   131.6    .045       0   141.6     .08       0
Bank Sta=131.6,141.6
XS Rating Curve= 0 ,0
Exp/Cntr=0.3,0.1

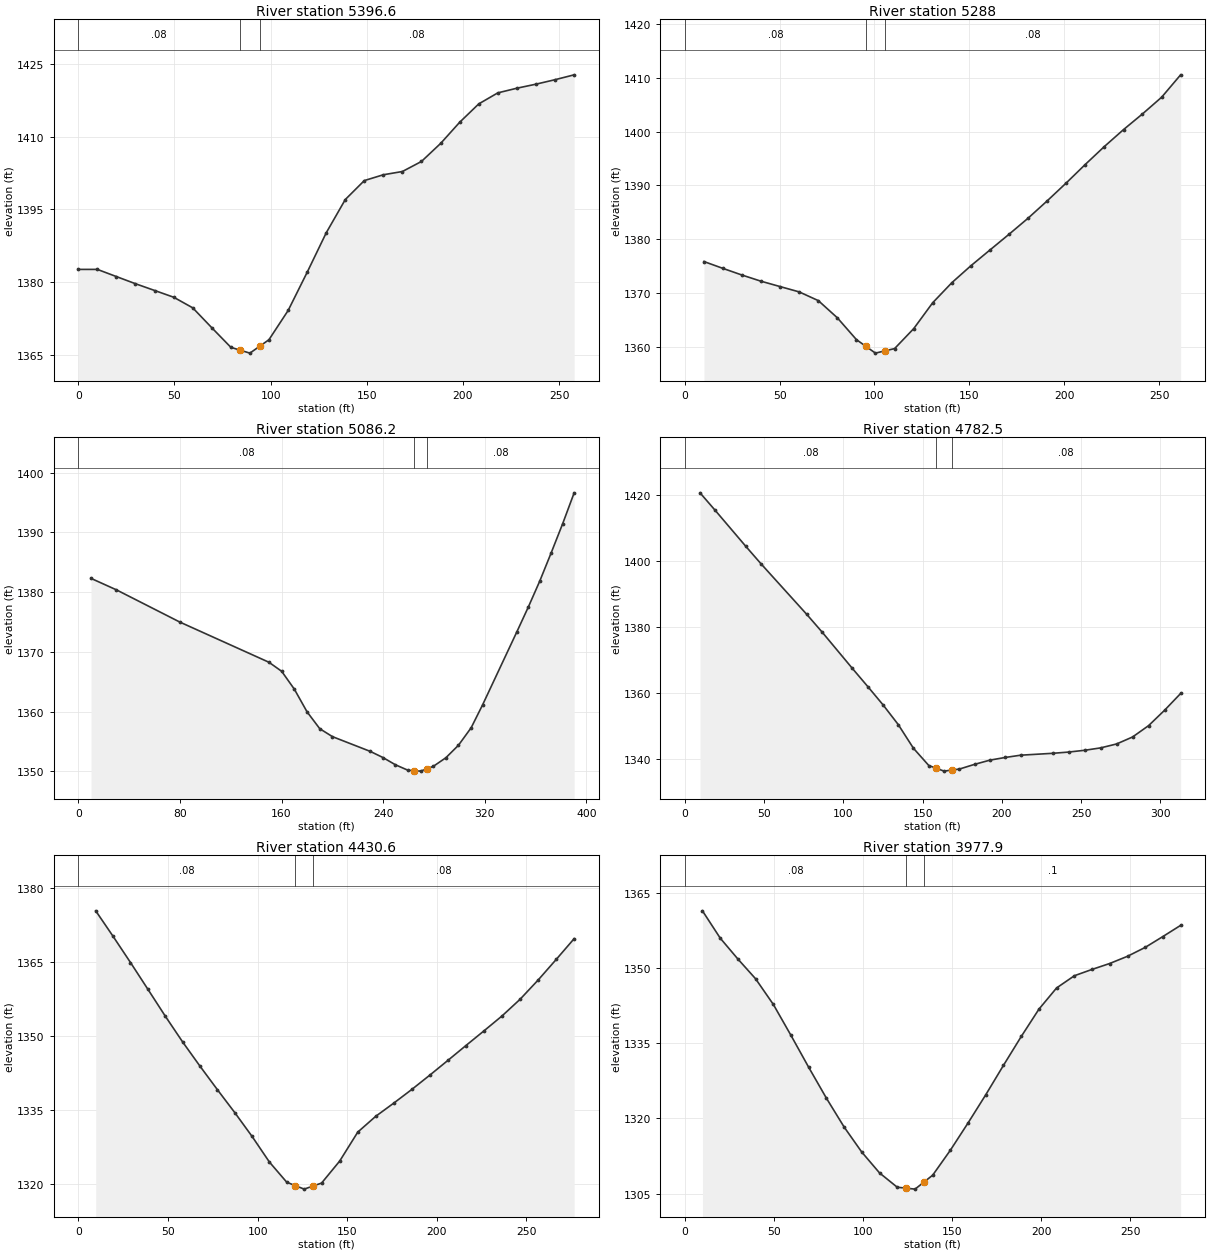
Type RM Length L Ch R = 1 ,5396.6  ,108.3,108.6,108.9
XS GIS Cut Line= 2
     1730997.365      131146.893     1731006.454      130889.298
#Sta/Elev= 29
       0 1382.65     9.9 1382.65    19.8 1381.17    29.7  1379.7    39.7  1378.3
    49.6 1376.91    59.5 1374.72    69.4 1370.62    79.3 1366.59    84.2 1365.99
    89.2 1365.39    94.2 1366.78    99.1 1368.15   109.1 1374.19     119 1382.07
   128.9  1390.2   138.8 1397.05   148.7 1400.96   158.6 1402.16   168.5 1402.83
   178.4  1404.9   188.4 1408.63   198.3 1412.99   208.2 1416.77   218.1 1419.04
     228    1420   237.9 1420.83   247.8 1421.75   257.8 1422.76
#Mann= 3 , 0 , 0
       0     .08       0    84.2    .045       0    94.2     .08       0
Bank Sta=84.2,94.2
XS Rating Curve= 0 ,0
Exp/Cntr=0.3,0.1

Type RM Length L Ch R = 1 ,5288    ,187,201.7,215.9
XS GIS Cut Line= 2
     1731104.328      131147.271     1731113.495      130886.008
#Sta/Elev= 28
    10.1 1375.88    20.1 1374.61    30.2 1373.37    40.2 1372.23    50.3 1371.23
    60.3 1370.25    70.4 1368.63    80.4 1365.45    90.5 1361.39    95.5 1360.14
   100.5 1358.89   105.5 1359.31   110.6 1359.73   120.7 1363.44   130.7 1368.24
   140.8 1371.96   150.8 1375.09   160.9 1378.03   170.9 1380.93     181 1383.93
     191 1387.12   201.1 1390.46   211.1 1393.88   221.2 1397.22   231.3 1400.36
   241.3 1403.27   251.4 1406.37   261.4 1410.52
#Mann= 3 , 0 , 0
       0     .08       0    95.5    .045       0   105.5     .08       0
Bank Sta=95.5,105.5
XS Rating Curve= 0 ,0
Exp/Cntr=0.3,0.1

Type RM Length L Ch R = 1 ,5086.2  ,329.2,303.7,278.8
XS GIS Cut Line= 4
     1731125.718      131229.775     1731260.169      131081.573
     1731335.033      131002.125     1731339.617      130921.149
#Sta/Elev= 27
      10 1382.29      30 1380.37      80 1374.97   150.1 1368.25   160.1 1366.74
   170.1 1363.74   180.1 1359.95   190.1 1357.13   200.1  1355.8   229.9 1353.33
   239.8 1352.31   249.7 1351.09   259.6 1350.17   264.6  1350.1   269.6 1350.03
   274.6 1350.43   279.5 1350.83   289.4 1352.27   299.3 1354.36   309.3 1357.29
   318.3 1361.12   345.3 1373.35   354.3 1377.49   363.3 1381.83   372.3 1386.56
   381.4 1391.47   390.4 1396.61
#Mann= 3 , 0 , 0
       0     .08       0   264.6    .045       0   274.6     .08       0
Bank Sta=264.6,274.6
XS Rating Curve= 0 ,0
Exp/Cntr=0.3,0.1

Type RM Length L Ch R = 1 ,4782.5  ,339.6,351.9,364.2
XS GIS Cut Line= 4
     1731568.794      131272.554     1731574.906      131138.103
     1731539.765       131069.35     1731536.709      130968.512
#Sta/Elev= 29
     9.6 1420.81    19.2 1415.48    38.5 1404.58    48.1 1399.28    76.9 1383.98
    86.5 1378.66   105.7 1367.58   115.4 1362.09     125 1356.56   134.6 1350.58
   144.2 1343.39   153.9 1338.15   158.5 1337.34   163.5 1336.46   168.5 1336.79
   173.2 1337.09   182.8 1338.52   192.5  1339.8   202.2 1340.61   211.8 1341.29
     232 1341.86   242.1 1342.24   252.2 1342.78   262.2  1343.5   272.3 1344.69
   282.4 1346.81   292.5 1350.25   302.6 1354.92   312.7 1359.99
#Mann= 3 , 0 , 0
       0     .08       0   158.5    .045       0   168.5     .08       0
Bank Sta=158.5,168.5
XS Rating Curve= 0 ,0
Exp/Cntr=0.3,0.1

Type RM Length L Ch R = 1 ,4430.6  ,455.8,452.7,449.6
XS GIS Cut Line= 3
     1731854.726      131144.269     1731872.174       131009.67
     1731889.557      130869.857
#Sta/Elev= 30
     9.7 1375.44    19.4 1370.25    29.1 1364.94    38.8 1359.51    48.5 1354.05
    58.2  1348.8    67.9 1343.87    77.6  1339.1    87.3 1334.44    96.9 1329.63
   106.6 1324.41   116.3  1320.3     121 1319.63     126 1318.91     131 1319.55
   135.7 1320.14   145.8 1324.61   155.9  1330.5   165.9  1333.7     176 1336.39
     186 1339.15   196.1 1342.07   206.2 1345.07   216.2 1348.07   226.3 1351.06
   236.4  1354.1   246.4 1357.46   256.5 1361.38   266.6 1365.57   276.6 1369.79
#Mann= 3 , 0 , 0
       0     .08       0     121    .045       0     131     .08       0
Bank Sta=121,131
XS Rating Curve= 0 ,0
Exp/Cntr=0.3,0.1

Type RM Length L Ch R = 1 ,3977.9  ,400.4,392.9,385.4
XS GIS Cut Line= 2
     1732322.025      131185.467     1732314.385      130907.398
#Sta/Elev= 30
     9.9 1361.43    19.9 1355.97    29.8 1351.81    39.7 1347.88    49.7 1342.74
    59.6 1336.56    69.5 1330.22    79.5 1324.02    89.4 1318.29    99.3 1313.29
   109.3 1309.12   119.2 1306.28   124.2 1306.09   129.2  1305.9   134.2 1307.31
   139.1 1308.69     149 1313.66     159 1319.14   168.9 1324.75   178.8  1330.6
   188.8 1336.37   198.7 1341.81   208.6 1346.04   218.6 1348.48   228.5 1349.74
   238.4 1350.92   248.4 1352.36   258.3 1354.13   268.2 1356.29   278.2 1358.53
#Mann= 3 , 0 , 0
       0     .08       0   124.2    .045       0   134.2      .1       0
Bank Sta=124.2,134.2
XS Rating Curve= 0 ,0
Exp/Cntr=0.3,0.1

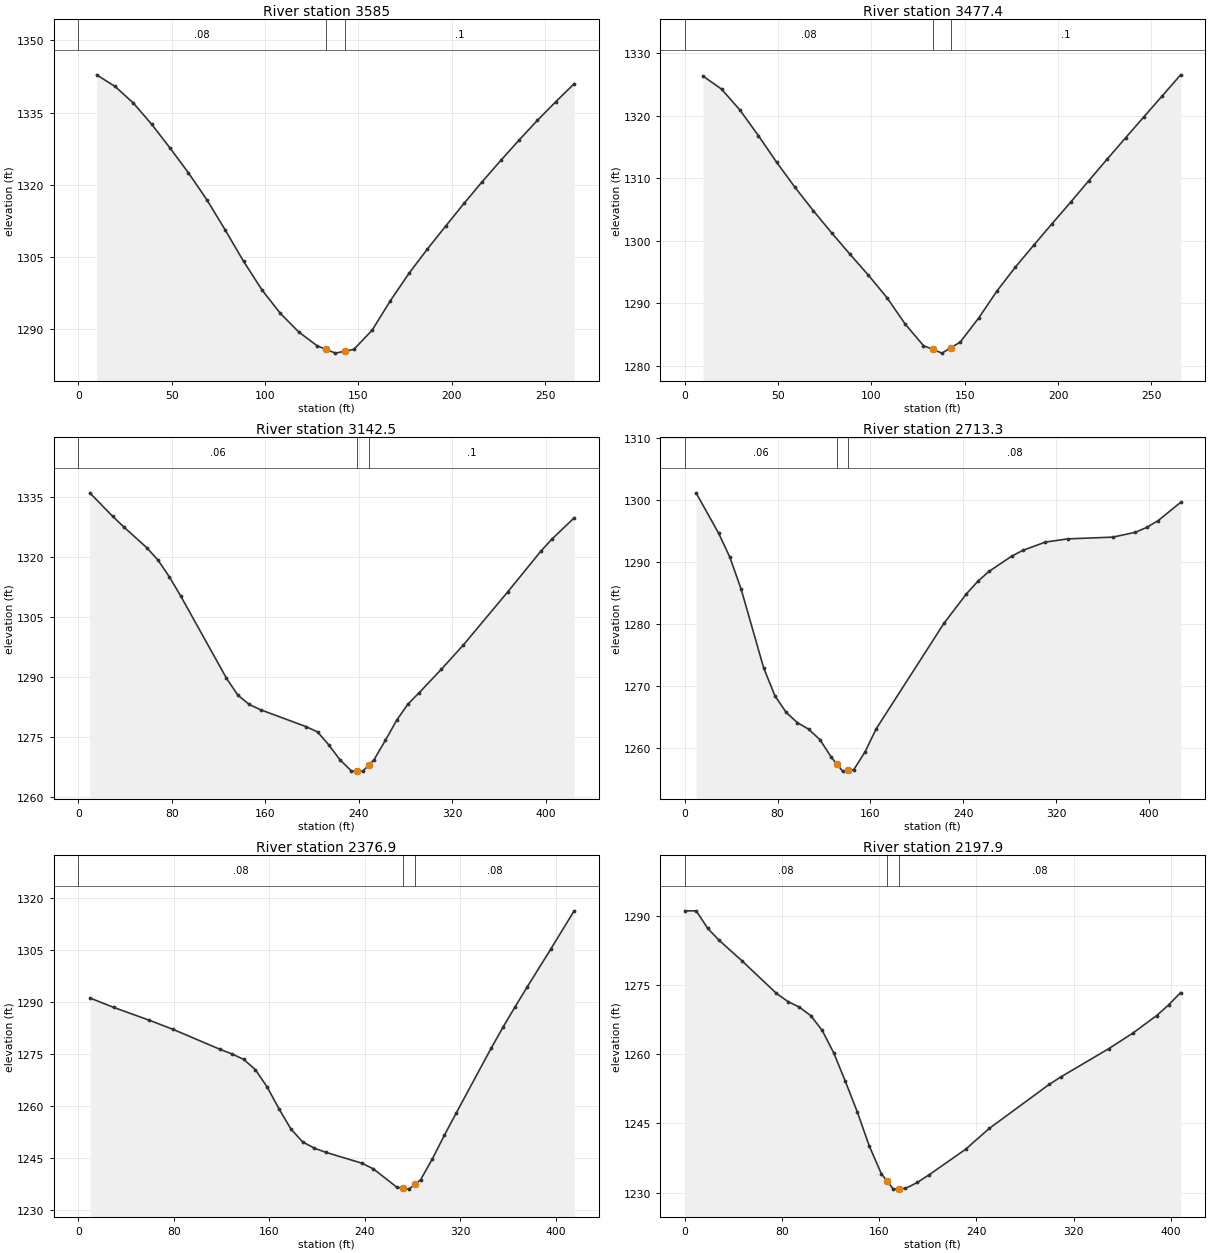
Type RM Length L Ch R = 1 ,3585    ,104.7,107.6,110.4
XS GIS Cut Line= 2
     1732749.823      131089.212     1732645.929      130844.756
#Sta/Elev= 29
     9.8 1342.86    19.7 1340.44    29.5 1336.98    39.4 1332.54    49.2 1327.61
      59 1322.49    68.9 1316.87    78.7 1310.61    88.5 1304.11    98.4 1298.15
   108.2  1293.3   118.1 1289.42   127.9 1286.56   132.7 1285.81   137.7 1285.03
   142.7 1285.42   147.6 1285.81   157.4 1289.81   167.2 1295.95   177.1  1301.6
   186.9 1306.62   196.8 1311.44   206.6 1316.14   216.4 1320.68   226.3 1325.07
   236.1 1329.31   245.9 1333.39   255.8 1337.29   265.6 1341.01
#Mann= 3 , 0 , 0
       0     .08       0   132.7    .045       0   142.7      .1       0
Bank Sta=132.7,142.7
XS Rating Curve= 0 ,0
Exp/Cntr=0.3,0.1

Type RM Length L Ch R = 1 ,3477.4  ,310.9,334.9,358.9
XS GIS Cut Line= 2
     1732830.799      131054.072     1732762.045      130797.393
#Sta/Elev= 29
     9.8 1326.35    19.7 1324.27    29.5 1320.94    39.4 1316.84    49.2 1312.57
    59.1 1308.52    68.9 1304.79    78.7 1301.25    88.6  1297.8    98.4 1294.47
   108.3 1290.89   118.1 1286.65   127.9 1283.19   132.8  1282.6   137.8 1281.99
   142.8 1282.89   147.6 1283.76   157.5 1287.62   167.3 1291.95   177.2 1295.79
     187 1299.28   196.8 1302.72   206.7 1306.14   216.5 1309.61   226.4 1313.08
   236.2 1316.47     246 1319.83   255.9  1323.2   265.7 1326.56
#Mann= 3 , 0 , 0
       0     .08       0   132.8    .045       0   142.8      .1       0
Bank Sta=132.8,142.8
XS Rating Curve= 0 ,0
Exp/Cntr=0.3,0.1

Type RM Length L Ch R = 1 ,3142.5  ,452.2,429.2,406.2
XS GIS Cut Line= 4
     1732961.284         131209.     1733044.698      131021.987
     1733108.081      130977.415     1733118.035      130835.589
#Sta/Elev= 30
     9.8 1335.93    29.3 1330.09      39 1327.38    58.5 1322.25    68.3 1319.09
      78  1314.9    87.8 1310.07   126.8 1289.61   136.5  1285.4   146.3 1283.05
     156 1281.73     195 1277.51   204.8 1276.18   214.5 1272.91   224.1 1269.17
   233.8 1266.43   238.5 1266.42   243.5  1266.4   248.5 1267.89   253.2  1269.3
   262.9 1274.13   272.6 1279.17   282.3 1283.21   291.7 1285.98   310.7 1291.84
   329.6 1297.93   367.6  1311.2     396 1321.39   405.5  1324.4   424.4 1329.68
#Mann= 3 , 0 , 0
       0     .06       0   238.5    .045       0   248.5      .1       0
Bank Sta=238.5,248.5
XS Rating Curve= 0 ,0
Exp/Cntr=0.3,0.1

Type RM Length L Ch R = 1 ,2713.3  ,330.6,336.4,342.1
XS GIS Cut Line= 3
     1733418.527      131268.156     1733381.175      131077.533
     1733383.751      130844.406
#Sta/Elev= 30
     9.7  1301.2    29.1 1294.71    38.8 1290.84    48.6 1285.65      68 1272.97
    77.7 1268.48    87.4  1265.8    97.1 1264.15   106.8 1263.09   116.5 1261.41
   126.3 1258.58     131 1257.49     136 1256.34     141 1256.47   145.7 1256.58
   155.4 1259.46   165.1  1263.2   223.4 1280.17   242.8 1284.92   252.5 1286.92
   262.2 1288.53   281.7 1290.98   291.4 1291.93   310.8 1293.26   330.2 1293.78
   369.1 1294.06   388.5 1294.85   398.2 1295.63     408 1296.72   427.4 1299.66
#Mann= 3 , 0 , 0
       0     .06       0     131    .045       0     141     .08       0
Bank Sta=131,141
XS Rating Curve= 0 ,0
Exp/Cntr=0.3,0.1

Type RM Length L Ch R = 1 ,2376.9  ,162.1,179.1,196
XS GIS Cut Line= 2
     1733638.841      131216.979     1733669.398      130802.549
#Sta/Elev= 30
     9.9 1291.23    29.7 1288.53    59.4 1284.84    79.2 1282.22   118.7 1276.43
   128.6 1275.12   138.5 1273.54   148.4 1270.56   158.3 1265.53   168.2 1259.24
   178.1 1253.46     188 1249.69   197.9 1247.87   207.8 1246.64   237.5 1243.56
   247.4 1241.88   267.1 1236.56     272 1236.31     277 1236.05     282 1237.42
   286.9 1238.76   296.8 1244.82   306.7 1251.54   316.6 1257.94   346.3 1276.92
   356.2 1282.96   366.1 1288.72     376 1294.31   395.8 1305.27   415.6 1316.43
#Mann= 3 , 0 , 0
       0     .08       0     272    .045       0     282     .08       0
Bank Sta=272,282
XS Rating Curve= 0 ,0
Exp/Cntr=0.3,0.1

Type RM Length L Ch R = 1 ,2197.9  ,261,246.8,232.5
XS GIS Cut Line= 4
     1733709.358      131219.336     1733744.499        131092.1
     1733822.101      131030.663     1733840.508      130854.646
#Sta/Elev= 30
       0 1291.14     9.4 1291.14    18.9 1287.32    28.3 1284.74    47.1 1280.28
    75.4 1273.23    84.9 1271.45    94.3 1270.24   103.7 1268.39   113.1 1265.18
   122.6 1260.29     132 1254.22   141.9 1247.54   151.8 1240.12   161.7 1234.11
   166.6 1232.45   171.6 1230.76   176.6 1230.83   181.5  1230.9   191.4 1232.21
   201.3 1233.92     231 1239.39   250.6 1243.94   299.8 1253.47   309.6 1255.13
     349 1261.26   368.6 1264.59   388.3 1268.42   398.1 1270.72     408 1273.41
#Mann= 3 , 0 , 0
       0     .08       0   166.6    .045       0   176.6     .08       0
Bank Sta=166.6,176.6
XS Rating Curve= 0 ,0
Exp/Cntr=0.3,0.1

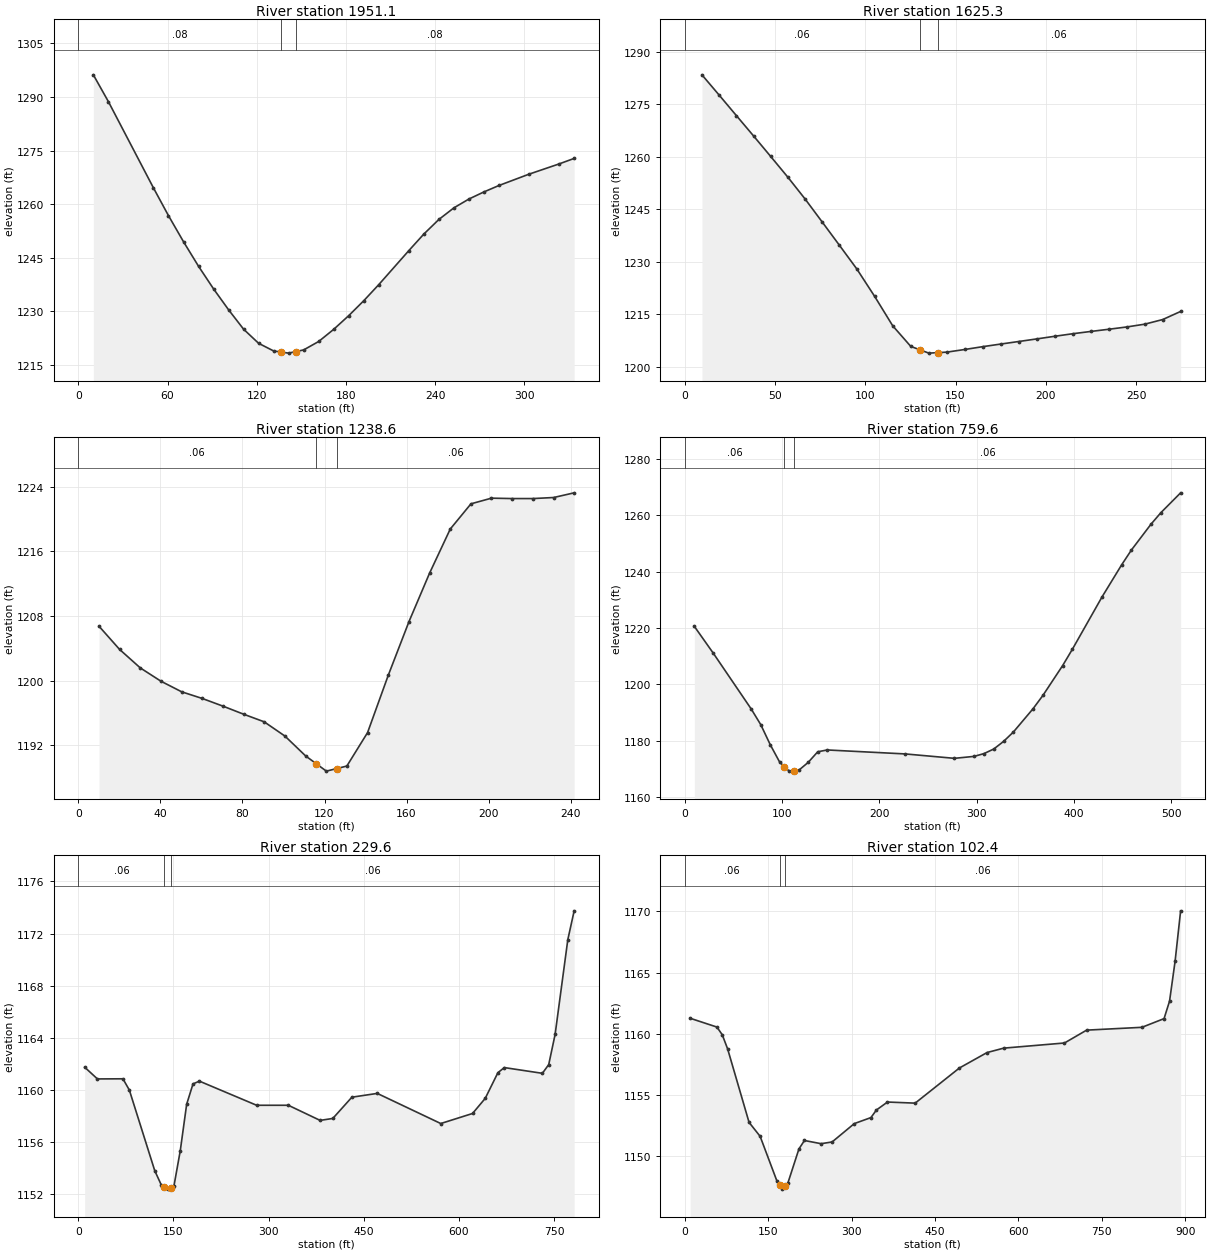
Type RM Length L Ch R = 1 ,1951.1  ,325.4,325.8,326.2
XS GIS Cut Line= 2
     1733994.066      131251.355     1734039.901      130920.958
#Sta/Elev= 30
    10.1 1296.21    20.2 1288.72    50.5 1264.56    60.6 1256.79    70.8 1249.42
    80.9 1242.55      91 1236.22   101.1 1230.37   111.2 1224.93   121.3 1220.98
   131.4 1218.84   136.5 1218.53   141.5 1218.23   146.5 1218.68   151.6 1219.13
   161.7 1221.49   171.8 1224.89   181.9 1228.72   192.1 1232.94   202.2 1237.45
   222.4 1246.97   232.5 1251.61   242.6 1255.69   252.7 1258.94   262.8 1261.41
   272.9  1263.4     283  1265.2   303.2 1268.37   323.5 1271.25   333.6 1272.79
#Mann= 3 , 0 , 0
       0     .08       0   136.5    .045       0   146.5     .08       0
Bank Sta=136.5,146.5
XS Rating Curve= 0 ,0
Exp/Cntr=0.3,0.1

Type RM Length L Ch R = 1 ,1625.3  ,382,386.7,391.3
XS GIS Cut Line= 3
     1734273.847      131261.849      1734315.36      131176.097
     1734354.535      131000.957
#Sta/Elev= 30
     9.5 1283.39    19.1 1277.56    28.6 1271.73    38.1 1265.93    47.6 1260.06
    57.2 1254.08    66.7 1247.88    76.2 1241.29    85.7 1234.67    95.3 1227.93
   105.2 1220.08   115.2 1211.68   125.2  1205.8   130.2 1204.84   135.2 1203.88
   140.2 1204.02   145.1 1204.16   155.1 1204.92   165.1 1205.73     175 1206.47
     185  1207.2     195 1207.94   204.9 1208.69   214.9 1209.42   224.9 1210.07
   234.9  1210.7   244.8 1211.35   254.8 1212.15   264.8 1213.48   274.7 1215.79
#Mann= 3 , 0 , 0
       0     .06       0   130.2    .045       0   140.2     .06       0
Bank Sta=130.2,140.2
XS Rating Curve= 0 ,0
Exp/Cntr=0.3,0.1

Type RM Length L Ch R = 1 ,1238.6  ,477.1,479,481
XS GIS Cut Line= 2
     1734643.402      131266.634     1734748.442      131048.915
#Sta/Elev= 26
    10.1 1206.73    20.1 1203.87    30.2 1201.58    40.3 1199.93    50.4 1198.62
    60.4  1197.8    70.5 1196.85    80.6 1195.85    90.6 1194.91   100.7 1193.15
   110.8 1190.69   115.9 1189.74   120.9 1188.81   125.9 1189.12   130.9 1189.44
     141 1193.58   151.1 1200.68   161.2 1207.32   171.2 1213.29   181.3 1218.76
   191.4 1221.88   201.4 1222.58   211.5 1222.53   221.6 1222.53   231.7 1222.66
   241.7 1223.24
#Mann= 3 , 0 , 0
       0     .06       0   115.9    .045       0   125.9     .06       0
Bank Sta=115.9,125.9
XS Rating Curve= 0 ,0
Exp/Cntr=0.3,0.1

Type RM Length L Ch R = 1 ,759.6   ,516.2,530,543.7
XS GIS Cut Line= 3
     1734982.098      131561.081     1735068.568      131419.536
     1735283.905      131151.875
#Sta/Elev= 30
     9.8 1220.61    29.3 1211.07    68.3 1191.26    78.1  1185.7    87.8 1178.62
    97.6 1172.36   102.3 1170.85   107.3 1169.25   112.3 1169.41   117.1 1169.56
   126.8 1172.36   136.6 1176.12   146.4 1176.76   226.5 1175.35     277 1173.79
   297.2 1174.48   307.3 1175.46   317.4 1177.09   327.5 1179.79   337.6 1183.13
   357.8 1191.39   367.9  1196.1   388.2  1206.7   398.3 1212.55   428.6 1231.02
   448.8 1242.43   458.9 1247.72   479.1 1256.91   489.2 1260.97   509.4 1267.98
#Mann= 3 , 0 , 0
       0     .06       0   102.3    .045       0   112.3     .06       0
Bank Sta=102.3,112.3
XS Rating Curve= 0 ,0
Exp/Cntr=0.3,0.1

Type RM Length L Ch R = 1 ,229.6   ,137.2,127.1,117.1
XS GIS Cut Line= 3
     1735160.708      131949.312     1735368.249      131873.383
      1735539.09      131339.346
#Sta/Elev= 30
      10 1161.76    30.1 1160.86    70.3 1160.87    80.4 1160.01   120.5 1153.82
   130.6 1152.75   135.6 1152.58   140.6 1152.41   145.6 1152.53   150.7 1152.64
   160.7 1155.35   170.8 1158.92   180.8 1160.48   190.9 1160.69   281.1 1158.84
   331.1 1158.84   381.2 1157.68   401.2 1157.83   431.3 1159.46   471.3 1159.75
   571.4 1157.44   621.5 1158.21   641.5 1159.37   661.5 1161.34   671.6 1161.73
   731.6 1161.29   741.6 1161.96   751.7 1164.28   771.7 1171.54   781.7 1173.75
#Mann= 3 , 0 , 0
       0     .06       0   135.6    .045       0   145.6     .06       0
Bank Sta=135.6,145.6
XS Rating Curve= 0 ,0
Exp/Cntr=0.3,0.1

Type RM Length L Ch R = 1 ,102.4   ,98.1,102.4,106.8
XS GIS Cut Line= 4
     1735208.707      132030.559     1735323.296      132045.838
     1735468.442      131881.594     1735565.653      131332.999
#Sta/Elev= 30
     9.6 1161.28    57.8 1160.56    67.4 1159.93    77.1 1158.77   115.6 1152.78
   135.5 1151.64   165.4 1148.03   170.4 1147.68   175.4 1147.33   180.4 1147.57
   185.3 1147.81   205.3 1150.61   215.2  1151.3   245.1 1151.04     265 1151.18
   304.9 1152.68   334.8 1153.17   344.7 1153.79   364.6 1154.44   414.4 1154.35
     494 1157.22   543.7 1158.48   573.6 1158.84     683 1159.26   722.8 1160.31
   822.3 1160.54   862.1 1161.25     872 1162.68     882 1165.95   891.9 1170.05
#Mann= 3 , 0 , 0
       0     .06       0   170.4    .045       0   180.4     .06       0
Bank Sta=170.4,180.4
XS Rating Curve= 0 ,0
Exp/Cntr=0.3,0.1
Stream Node=Oozley Branch   ,Main            , 0 , 0 ,Upstream end
Stream Node=Oozley Branch   ,Main            , 0 , 1 ,Downstream end

Chan Stop Cuts=-1
Use User Specified Reach Order=0